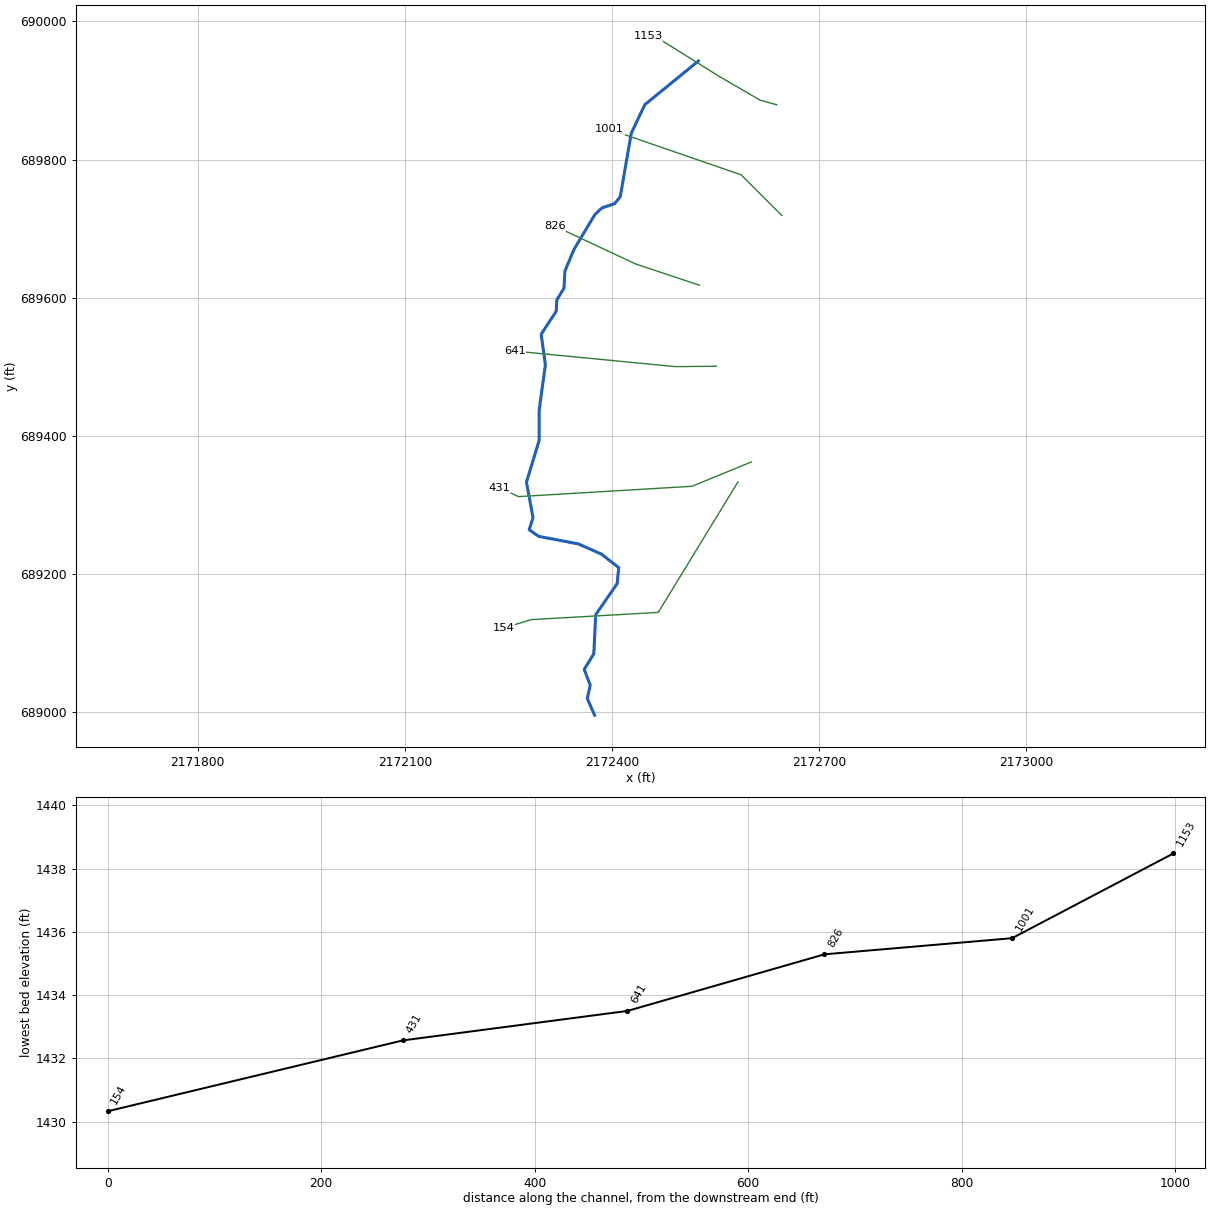
--- MORGANRN.prj (project) ---

Proj Title=MORGANRN
Current Plan=p01
Default Exp/Contr=0.3,0.1
English Units
Geom File=g01
Flow File=f01
Plan File=p01
Y Axis Title=Elevation
X Axis Title(PF)=Main Channel Distance
X Axis Title(XS)=Station
BEGIN DESCRIPTION:
---------- MODELED AS PART OF WVEMD CTP PROGRAM, 2023----------
Stream Name: Morgan Run
Flood Zone:  AFH
Upshur County, WV
HEC-RAS Version: RAS 6.3
Vertical Datum: NAVD88
Projection: NAD 1983 StatePlane West Virginia S FIPS 4702 (US Feet)
Terrain: 1-meter LIDAR (FEMA Region III 3DEP collected 2016-2018)
Land Use: 2019 NLCD
Hydrologic Method:
WV SIR2010-5033 regression equations
Additional Model Notes:
None
END DESCRIPTION:
DSS Export Rating Curves= 0
DSS Export Rating Curve Sorted= 0
DSS Export Volume Flow Curves= 0
DXF OffsetX= 0
DXF OffsetY= 0
DXF ScaleX= 1
DXF ScaleY= 10

--- MORGANRN.p01 (plan) ---

Plan Title=Floodplain
Program Version=6.30
Short Identifier=Floodplain
Geom File=g01
Flow File=f01
Subcritical Flow
K Sum by GR= 0
Std Step Tol= 0.01
Critical Tol= 0.01
Num of Std Step Trials= 20
Max Error Tol= 0.3
Flow Tol Ratio= 0.001
Split Flow NTrial= 30
Split Flow Tol= 0.02
Split Flow Ratio= 0.02
Log Output Level= 0
Friction Slope Method= 1
Unsteady Friction Slope Method= 2
Unsteady Bridges Friction Slope Method= 1
Parabolic Critical Depth
Global Vel Dist= 0 , 0 , 0
Global Log Level= 0
CheckData=True
Encroach Param=-1 ,0,0, 0
Computation Interval=1MIN
Output Interval=1HOUR
Instantaneous Interval=1HOUR
Mapping Interval=1HOUR
Computation Time Step Use Courant=        0
Computation Time Step Use Time Series=    0
Computation Time Step Count To Double=0
Computation Time Step Max Doubling=0
Computation Time Step Max Halving=0
Computation Time Step Residence Courant=0
Run HTab= 0
Run UNet= 0
Run Sediment= 0
Run PostProcess= 0
Run WQNet= 0
Run RASMapper=-1
UNET Theta= 1
UNET Theta Warmup= 1
UNET ZTol= 0.02
UNET ZSATol= 0.02
UNET MxIter= 20
UNET Max Iter WO Improvement= 0
UNET MaxInSteps= 0
UNET DtIC= 0
UNET DtMin= 0
UNET MaxCRTS= 20
UNET WFStab= 2
UNET SFStab= 1
UNET WFX= 1
UNET SFX= 1
UNET Gravity=32.17405
UNET 1D Methodology=Finite Difference
UNET DSS MLevel= 4
UNET Pardiso=0
UNET DZMax Abort= 100
UNET Use Existing IB Tables=-1
UNET Froude Reduction=False
UNET Froude Limit= 0.8
UNET Froude Power= 4
UNET D1 Cores= 0
UNET WindReference=Eulerian
UNET WindDragFormulation=Hsu (1988)
UNET D2 Coriolis=0
UNET D2 Cores= 0
UNET D2 Theta= 1
UNET D2 Theta Warmup= 1
UNET D2 Z Tol= 0.01
UNET D2 Volume Tol= 0.01
UNET D2 Max Iterations= 20
UNET D2 Equation= 0
UNET D2 RampUpFraction=0.1
UNET D2 TimeSlices= 1
UNET D2 Turbulence Formulation=None
UNET D2 Eddy Viscosity=0.3
UNET D2 Transverse Eddy Viscosity=0.1
UNET D2 Smagorinsky Mixing=0.05
UNET D2 BCVolumeCheck=0
UNET D2 Cores=0
UNET D2 SolverType=PARDISO (Direct)
UNET D2 Minimum Iterations= 3
UNET D2 Maximum Iterations= 30
UNET D2 Restart Number= 10
UNET D2 Relaxation Coeff=1.3
UNET D2 SOR Precondition Iterations= 10
UNET D2 ILUT Maximum Fill= 8
UNET D2 ILUT Tolerance=1E-08
UNET D2 Convergence Tolerance=0.00001
UNET D1D2 MaxIter= 0
UNET D1D2 ZTol=0.01
UNET D1D2 QTol=0.1
UNET D1D2 MinQTol=1
Write IC File= 0
Write IC File at Fixed DateTime=0
Write IC File at Sim End=0
Echo Input=False
Echo Parameters=False
Echo Output=False
Write Detailed= 0
HDF Write Warmup=0
HDF Write Time Slices=0
HDF Flush=0
HDF Compression= 1
HDF Chunk Size= 1
HDF Spatial Parts= 1
HDF Use Max Rows=0
HDF Fixed Rows= 1
Calibration Method= 0
Calibration Iterations= 20
Calibration Max Change=0.05
Calibration Tolerance=0.2
Calibration Maximum=1.5
Calibration Minimum=0.5
Calibration Optimization Method= 1
WQ AD Non Conservative
WQ ULTIMATE=-1
WQ Max Comp Step=1HOUR
WQ Output Interval=15MIN
WQ Output Selected Increments= 0
WQ Output face flow=0
WQ Output face velocity=0
WQ Output face area=0
WQ Output face dispersion=0
WQ Output cell volume=0
WQ Output cell surface area=0
WQ Output cell continuity=0
WQ Output cumulative cell continuity=0
WQ Output face conc=0
WQ Output face dconc_dx=0
WQ Output face courant=0
WQ Output face peclet=0
WQ Output face adv mass=0
WQ Output face disp mass=0
WQ Output cell mass=0
WQ Output cell source sink temp=0
WQ Output nsm pathways=0
WQ Output nsm derived pathways=0
WQ Create Restart=0
WQ Fixed Restart=0
WQ System Summary=0
WQ Write To DSS=0
Sorting and Armoring Iterations= 10
XS Update Threshold= 0.02
Bed Roughness Predictor= 0
Hydraulics Update Threshold= 0.02
Energy Slope Method= 1
Volume Change Method= 1
Sediment Retention Method= 0
Sediment TS Multiplier= 1
Warm Up Method= 0
XS Weighting Method= 0
Number of US Weighted Cross Sections= 1
Number of DS Weighted Cross Sections= 1
Upstream XS Weight=0
Main XS Weight=1
Downstream XS Weight=0
Number of DS XS's Weighted with US Boundary= 1
Upstream Boundary Weight= 1
Weight of XSs Associated with US Boundary= 0
Number of US XS's Weighted with DS Boundary= 1
Downstream Boundary Weight= 0.5
Weight of XSs Associated with DS Boundary= 0.5
Percentile Method= 0
Sediment Output Level= 3
Mass or Volume Output= 0
Output Increment Type= 1
Profile and TS Output Increment= 1
Transport Output Increment 1
XS Output Flag= 0
XS Output Increment= 10
Read HDF5 Sediment Hotstart= 0
Sediment Hotstart Type= 0
Write Gradation File= 0
Read Gradation Hotstart= 0
Write HDF5 File= 1
Write Binary Output= 1
Write DSS Sediment File= 0
DSS Sediment Output Type= 1
SV Curve= 0
Specific Gage Flag= 0
Subcell Erosion Methods= 0
Subcell Deposition Methods= 0
Advection Scheme= 1
Matrix Solver= 0
Implicit Weighting Factor= 1
Maximum Outer Loop Convergence Iterations= 5
Convergence Maximum Absolute= 0.001
Convergence RMSE= 0.0001
Grain Fractions Max Abs Error= 0.001
Max Subgrid Regions= 1
Max Subgrid Length Scale= 3.402823E+38
Initial Layer Thickness= 3.402823E+38
Min Layer Thickness= 3.402823E+38
Max Layer Thickness= 3.402823E+38
Number of Layers= 5

--- MORGANRN.f01 (steady flow) ---

Flow Title=Flows
Program Version=6.31
Number of Profiles= 1
Profile Names=01pct
River Rch & RM=MORGANRN,Main            ,1153
     175
Boundary for River Rch & Prof#=MORGANRN,Main            , 1
Up Type= 0
Dn Type= 3
Dn Slope=0.01101
DSS Import GetInterval= 0
DSS Import GetPeak= 0
DSS Import FillOption= 0

--- MORGANRN.g01 (geometry) ---

Geom Title=Geometry
Program Version=6.31

River Reach=MORGANRN        ,Main
Reach XY= 30
2172525.48761173689942.7426451612172447.81418831689879.430221922
2172428.18187259689837.9644913592172412.24605589689746.045059611
2172404.09369381689736.0113831992172385.80313785689729.844852904
2172375.35139159689720.020211417 2172345.4004088 689670.05280986
 2172332.0665935689638.4326193052172330.73347615689613.724010898
2172320.33235289689596.4560576922172319.46832166689580.224613851
2172297.66200876689546.7817173982172303.77744393689502.499394117
2172294.66428577689436.3198568182172294.70984987 689392.82327506
2172276.33384262689332.4703987112172285.87171394689280.888825067
2172280.25551094689263.6082004452172293.73872126689254.014856877
2172351.48016853689242.9884205582172384.91424606689228.248358307
2172410.07420481689208.5930346152172407.75676489689185.418635502
2172376.70307008689140.4603012232172373.92729829689083.782695074
2172359.97708182689061.0359855412172368.73978139689038.258000156
2172364.44060885 689019.111685242172375.05865273688994.732542978

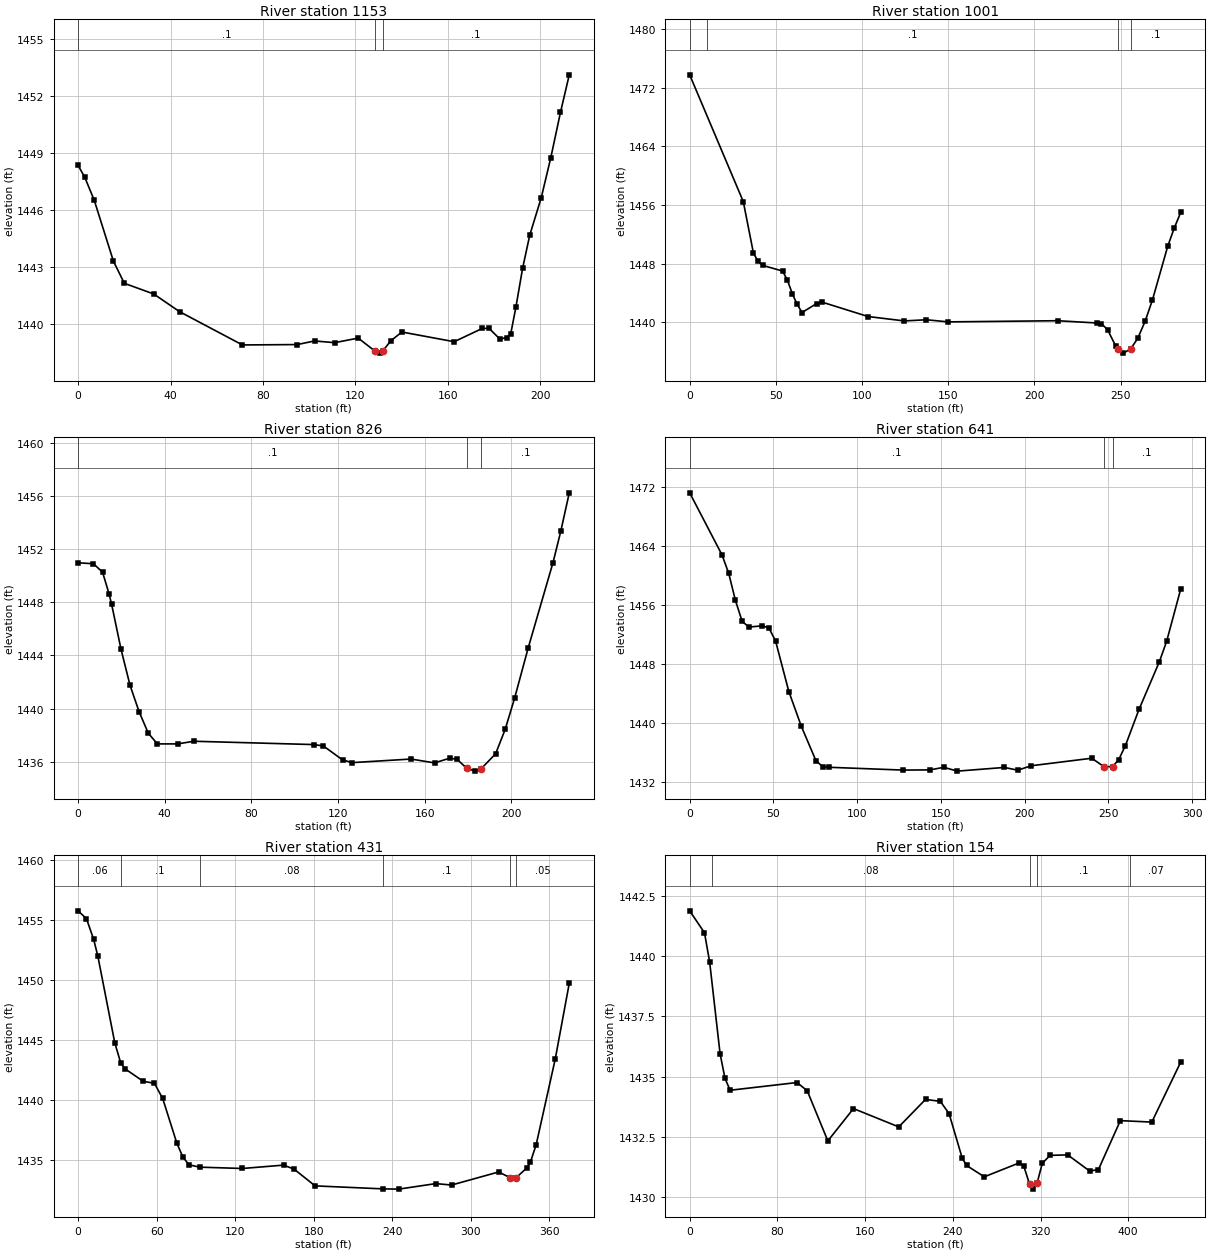
Type RM Length L Ch R = 1 ,1153    ,151.2,151.2,151.2
XS GIS Cut Line= 5
2172638.92240212689879.3195970872172615.19919057689885.884615232
2172556.82900545689919.7323174982172470.50009669689973.687885469
2172452.42498142689978.274108747
#Sta/Elev= 30
       0 1448.35     2.9 1447.72       7 1446.51    15.3 1443.31      20 1442.15
    32.7 1441.59    43.9 1440.66    71.1 1438.91    94.8 1438.93   102.3 1439.12
     111 1439.03   121.2 1439.27   128.4 1438.59   130.6 1438.48   131.81438.592
   135.3 1439.13   140.1 1439.59   162.7 1439.08   174.9 1439.78   177.8 1439.78
   182.5 1439.22   185.4  1439.3   187.2 1439.51   189.4 1440.89   192.3 1442.93
   195.4 1444.68   200.4 1446.66   204.5 1448.75   208.7 1451.14   212.5 1453.11
#Mann= 3 ,-1,0
       0      .1       0   128.4    .045       0   131.8      .1       0
Bank Sta=128.4,131.8
XS Rating Curve= 0 ,0
Exp/Cntr(USF)=0,0
Exp/Cntr=0.3,0.1

Type RM Length L Ch R = 1 ,1001    ,176,175.8,174.4
XS GIS Cut Line= 3
2172646.18352962689719.0496358822172587.38421382689777.848951686
2172396.59482548689843.638395943
#Sta/Elev= 30
       0 1473.75    31.1 1456.46      37 1449.43    39.7 1448.31    42.4 1447.76
    53.9 1446.99    56.7 1445.75    59.6 1443.87    62.3 1442.48    65.2 1441.34
    73.6 1442.55    76.6 1442.77   103.5 1440.79   124.6 1440.19   137.3 1440.35
     150 1440.06   213.5 1440.22   236.2 1439.91   238.9 1439.83   242.5 1438.99
   247.3 1436.71   248.8 1436.35   251.6  1435.8   255.8 1436.35     260 1437.82
   264.3 1440.17   268.5 1443.04   277.4 1450.39   281.2 1452.88     285 1455.03
#Mann= 4 ,-1,0
       0     .08       0      10      .1       0   248.8    .045       0
   255.8      .1       0
Bank Sta=248.8,255.8
XS Rating Curve= 0 ,0
Exp/Cntr(USF)=0,0
Exp/Cntr=0.3,0.1

Type RM Length L Ch R = 1 ,826     ,181.3,184.7,186.6
XS GIS Cut Line= 3
 2172526.9259457689617.8896086372172434.14243064689648.793845153
2172317.32356829689703.590613999
#Sta/Elev= 30
       0 1450.98     7.1 1450.91    11.3 1450.27    14.3 1448.64    15.5 1447.84
    19.8 1444.48      24 1441.74    28.2 1439.75    32.4 1438.15    36.6 1437.34
    45.9 1437.34    53.5 1437.54   108.8 1437.29   113.2 1437.19   122.1 1436.14
   126.5 1435.93   153.7  1436.2   164.6 1435.91   171.7 1436.27   175.1 1436.17
   179.5 1435.49   183.5 1435.29   186.21435.482   192.8  1436.6   197.2 1438.43
   201.6 1440.81   207.8 1444.55   219.3    1451   222.9 1453.37   226.8 1456.25
#Mann= 3 ,-1,0
       0      .1       0   179.5    .045       0   186.2      .1       0
Bank Sta=179.5,186.2
XS Rating Curve= 0 ,0
Exp/Cntr(USF)=0,0
Exp/Cntr=0.3,0.1

Type RM Length L Ch R = 1 ,641     ,209.1,210.2,211.4
XS GIS Cut Line= 3
2172551.46008206 689500.426438082172492.23604531689499.862399634
2172259.28816741689522.423937445
#Sta/Elev= 30
       0 1471.25    19.3 1462.83    23.3 1460.34    27.3 1456.66    31.3 1453.83
    35.3 1453.04    43.3 1453.21    47.3 1452.93    51.3 1451.14    59.2  1444.3
    66.7 1439.56    75.4 1434.91    79.4 1434.11    83.4 1434.02   127.6 1433.64
   143.7 1433.67   151.7 1434.02   159.8  1433.5   187.9    1434   195.9 1433.63
     204 1434.23   240.1 1435.25   247.3 1434.12   252.51434.099   256.2 1435.06
   260.2 1436.97   268.3 1441.87   280.4  1448.3   284.8  1451.1   293.3 1458.27
#Mann= 3 ,-1,0
       0      .1       0   247.3    .045       0   252.5      .1       0
Bank Sta=247.3,252.5
XS Rating Curve= 0 ,0
Exp/Cntr(USF)=0,0
Exp/Cntr=0.3,0.1

Type RM Length L Ch R = 1 ,431     ,215.7,276.7,215.7
XS GIS Cut Line= 4
2172602.08894759689361.6614425412172516.19717314689326.482364709
2172264.83582066689311.4997172812172237.30229432689324.676476313
#Sta/Elev= 30
       0 1455.75     6.4 1455.09    11.8  1453.4      15 1452.02      28 1444.76
    32.5  1443.1    35.6 1442.61    49.6 1441.56    58.3 1441.38    64.6 1440.12
    75.4  1436.4    79.9 1435.27    84.6  1434.6    92.8  1434.4   125.5 1434.29
     157 1434.57     165 1434.23     181 1432.84   233.1 1432.59   244.9 1432.57
   273.2 1433.03   285.2 1432.91   321.2    1434   330.1 1433.51   334.51433.517
   342.9 1434.36   345.4 1434.81   349.8 1436.26   364.4 1443.41   375.1 1449.72
#Mann= 6 ,-1,0
       0     .06       0    32.5      .1       0    92.8     .08       0
   233.1      .1       0   330.1    .045       0   334.5     .05       0
Bank Sta=330.1,334.5
XS Rating Curve= 0 ,0
Exp/Cntr(USF)=0,0
Exp/Cntr=0.3,0.1

Type RM Length L Ch R = 1 ,154     ,,,
XS GIS Cut Line= 4
2172582.74666775689332.6950129462172467.31932845689143.753756297
2172283.21996594689133.2643748652172242.82032382689120.965026994
#Sta/Elev= 30
       0 1441.87    13.5 1440.96    18.2 1439.75    27.7 1435.95    32.2 1434.92
    36.9 1434.43    97.9 1434.75   107.2 1434.41     126 1432.33   149.4 1433.67
   190.7 1432.91   215.1 1434.05   228.6 1433.97   236.6 1433.46   248.6 1431.61
   252.6 1431.31   268.7 1430.84   300.7 1431.42   304.7 1431.29     3101430.536
   312.7 1430.33   316.81430.566   321.6  1431.4   328.7 1431.73   344.8 1431.75
   364.8 1431.08   372.8 1431.14   392.8 1433.17   421.5 1433.11     448 1435.61
#Mann= 5 ,-1,0
       0     .06       0      20     .08       0     310    .045       0
   316.8      .1       0  401.41     .07       0
Bank Sta=310,316.8
XS Rating Curve= 0 ,0
Exp/Cntr(USF)=0,0
Exp/Cntr=0.3,0.1
LCMann Table=0

Chan Stop Cuts=-1
Use User Specified Reach Order=0
Composite Channel Slope=5